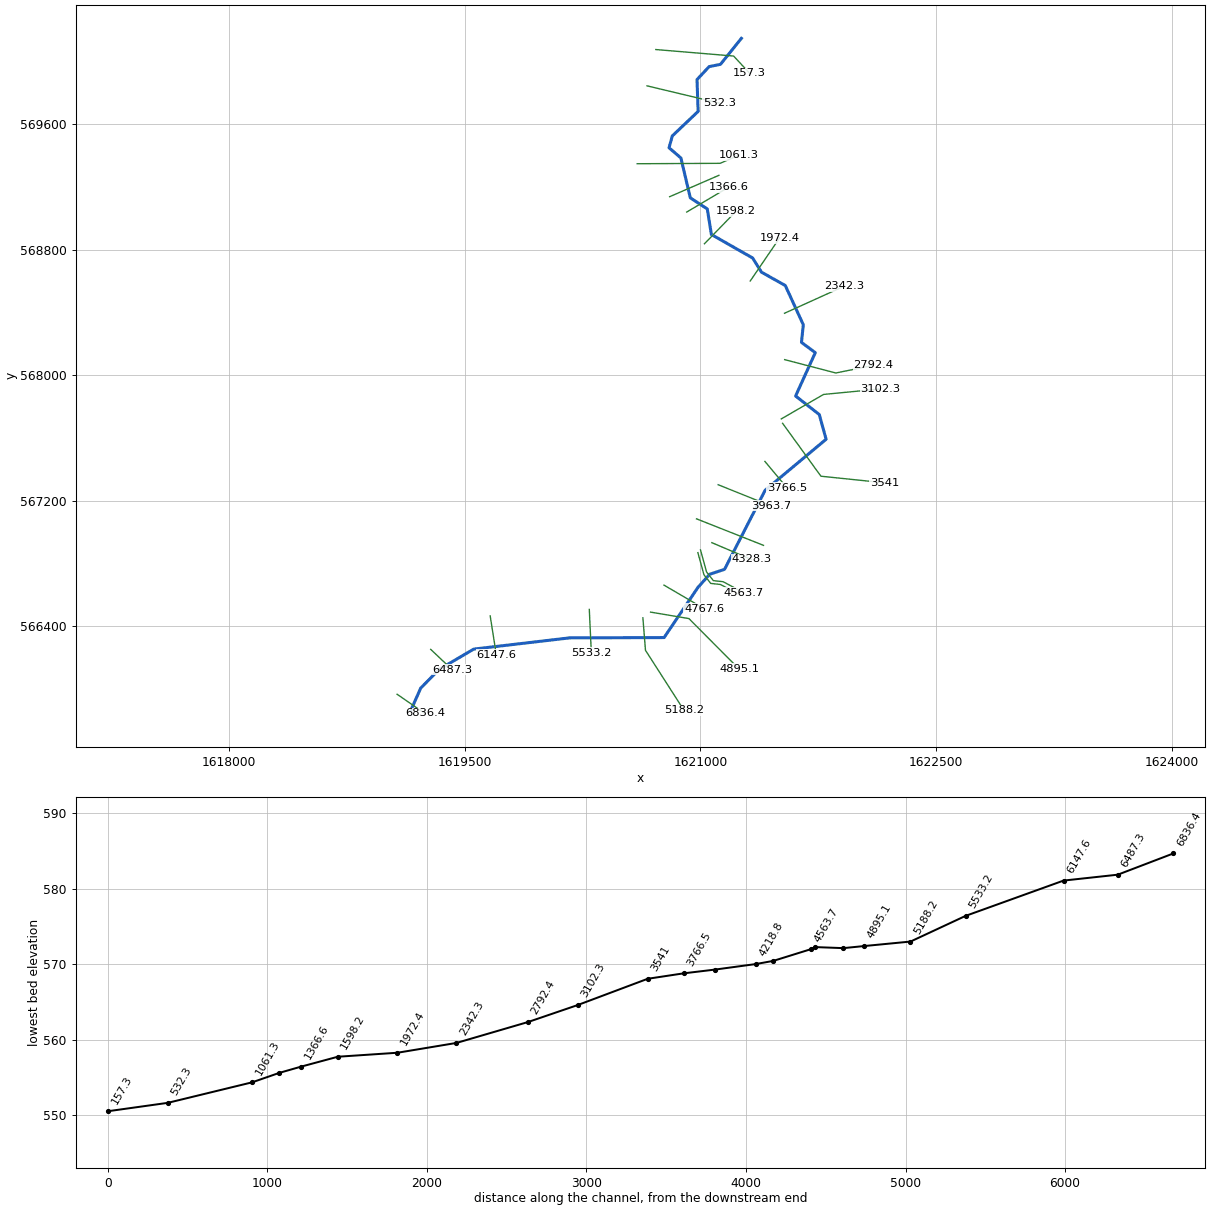
--- LFSpurlkCr.prj (project) ---

Proj Title=LFSpurlkCr
Current Plan=p01
Geom File=g01
Flow File=f01
Plan File=p01
DSS Export Rating Curves=0
DSS Export Rating Curve Sorted=0
DSS Export Volume Flow Curves=0
DXF OffsetX=0
DXF OffsetY=0
DXF ScaleX=0
DXF ScaleY=0

--- LFSpurlkCr.p01 (plan) ---

Plan Title=Floodplain
Program Version=4.00
Geom File=g01
Flow File=f01
K Sum by GR=0
Std Step Tol=0.01
Critical Tol=0.01
Num of Std Step Trials=20
Max Error Tol=0.3
Flow Tol Ratio=0.001
Split Flow NTrial=30
Split Flow Tol=0.02
Split Flow Ratio=0.02
Log Output Level=0
Friction Slope Method=1
Unsteady Friction Slope Method=2
Unsteady Bridges Friction Slope Method=1
Global Log Level=0
CheckData=False
Run HTab=0
Run UNet=0
Run PostProcess=0
UNET Theta=0
UNET Theta Warmup=0
UNET ZTol=0
UNET ZSATol=0
UNET MxIter=0
UNET MaxInSteps=0
UNET DtIC=0
UNET DtMin=0
UNET MaxCRTS=0
UNET WFStab=0
UNET SFStab=0
UNET WFX=0
UNET SFX=0
UNET DSS MLevel=0
UNET DZMax Abort=0
UNET Convert EG Bridges=0
UNET Use Existing IB Tables=0
UNET Froude Limit=0
UNET Froude Power=0
Write IC File=0
Echo Input=False
Echo Output=False
Write Detailed=0

--- LFSpurlkCr.f01 (steady flow) ---

Flow Title=NFF Regression Equation
Program Version=4.10
Number of Profiles= 1
Profile Names=P100yr
River Rch & RM=LFSpurlkCr,Main            ,6836.4
    1096
River Rch & RM=LFSpurlkCr,Main            ,5533.2
    1123
River Rch & RM=LFSpurlkCr,Main            ,4895.1
    1138
River Rch & RM=LFSpurlkCr,Main            ,4588.1
    1317
River Rch & RM=LFSpurlkCr,Main            ,3541
    1336
River Rch & RM=LFSpurlkCr,Main            ,2342.3
    1380
River Rch & RM=LFSpurlkCr,Main            ,1061.3
    1398
River Rch & RM=LFSpurlkCr,Main            ,532.3
    1413
River Rch & RM=LFSpurlkCr,Main            ,157.3
    1415
Boundary for River Rch & Prof#=LFSpurlkCr,Main            , 1
Up Type= 0
Dn Type= 3
Dn Slope=0.00296
DSS Import GetInterval= 0
DSS Import GetPeak= 0
DSS Import FillOption= 0

--- LFSpurlkCr.g01 (geometry) ---

Geom Title=USGS 10m DEM
Program Version=4.10

River Reach=LFSpurlkCr      ,Main
Reach XY= 30
     1619155.667      565859.521     1619219.557      566003.802
     1619337.802       566123.36     1619557.142      566252.316
     1620166.951       566323.93     1620768.844      566325.855
     1620985.353      566647.193     1621059.138      566729.658
     1621153.751      566761.196     1621412.283      567266.029
     1621800.223      567591.011     1621756.713        567748.8
     1621606.013      567866.811     1621731.386      568143.333
      1621643.46      568208.918     1621655.009      568321.519
       1621540.5      568571.458     1621388.999      568656.742
     1621332.511      568747.248     1621069.772      568897.193
     1621043.874      569060.156     1620935.836      569130.816
     1620875.778      569385.419     1620800.317      569450.438
     1620821.318      569526.059     1620985.617      569682.458
     1620978.398       569885.19     1621055.458      569967.954
     1621127.799      569982.619      1621260.89      570148.483

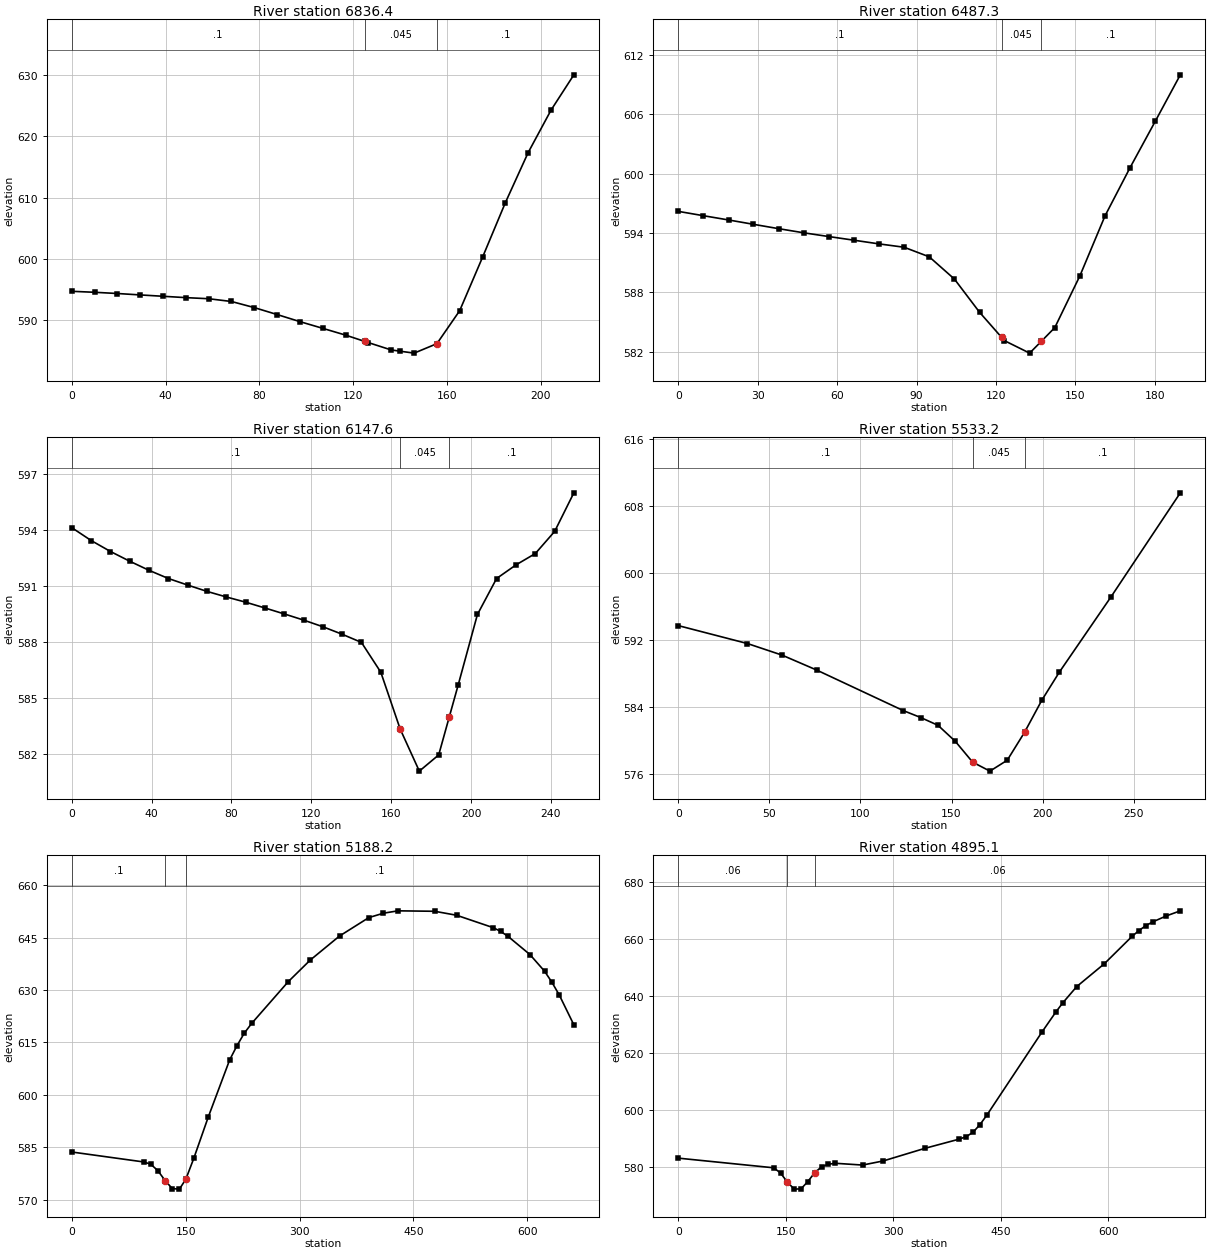
Type RM Length L Ch R = 1 ,6836.4  ,352.5,349.1,345.4
XS GIS Cut Line= 2
     1619069.313      565964.227     1619245.284      565842.312
#Sta/Elev= 25
       0  594.74     9.7  594.58    19.5  594.38    29.2  594.15    38.9  593.93
    48.6  593.71    58.4  593.53    68.1  593.08    77.8  592.09    87.6  590.95
    97.3   589.8     107  588.71   116.8   587.6   124.9  586.58   126.5  586.38
   136.2  585.19   139.9  584.99     146  584.67   155.7  586.21   165.4  591.57
   175.2  600.32   184.9  609.18   194.6  617.32   204.4  624.27   214.1     630
#Mann= 3 , 0 , 0
       0      .1       0   124.9    .045       0   155.7      .1       0
Bank Sta=124.9,155.7
XS Rating Curve= 0 ,0
Exp/Cntr=0.3,0.1

Type RM Length L Ch R = 1 ,6487.3  ,354.5,339.7,324.9
XS GIS Cut Line= 2
     1619283.072      566250.685     1619420.701      566120.263
#Sta/Elev= 23
       0  596.19     9.5  595.75      19  595.32    28.4  594.88    37.9  594.44
    47.4  594.02    56.9  593.64    66.4  593.27    75.8   592.9    85.3  592.56
    94.8  591.59   104.3  589.34   113.8  585.98   122.1  583.45   123.2  583.11
   132.7  581.85   137.1  583.04   142.2  584.43   151.7  589.68   161.2  595.75
   170.6   600.6   180.1  605.28   189.6     610
#Mann= 3 , 0 , 0
       0      .1       0   122.1    .045       0   137.1      .1       0
Bank Sta=122.1,137.1
XS Rating Curve= 0 ,0
Exp/Cntr=0.3,0.1

Type RM Length L Ch R = 1 ,6147.6  ,616.6,614.4,611.8
XS GIS Cut Line= 2
     1619661.761      566464.444     1619700.823      566215.963
#Sta/Elev= 28
       0  594.14     9.7  593.45    19.4  592.86      29  592.34    38.7  591.85
    48.4  591.41      58  591.06    67.7  590.72    77.4  590.42    87.1  590.14
    96.7  589.83   106.4  589.51   116.1  589.18   125.8  588.82   135.4  588.42
   145.1  587.98   154.8  586.38   164.5  583.33   174.1  581.07   183.8  581.94
   189.1  583.98   193.5  585.67   203.2  589.48   212.8  591.41   222.5  592.14
   232.2  592.75   241.9  593.94   251.5  596.01
#Mann= 3 , 0 , 0
       0      .1       0   164.5    .045       0   189.1      .1       0
Bank Sta=164.5,189.1
XS Rating Curve= 0 ,0
Exp/Cntr=0.3,0.1

Type RM Length L Ch R = 1 ,5533.2  ,344.4,345.1,345.8
XS GIS Cut Line= 2
     1620292.703      566505.336      1620305.69      566229.998
#Sta/Elev= 16
       0  593.74      38   591.6      57  590.22      76  588.44   123.6   583.6
   133.1  582.78   142.6  581.85   152.1  579.94   161.6  577.46   171.1  576.39
   180.6  577.69   190.1  581.02   199.6  584.85   209.1  588.16   237.6  597.18
   275.6  609.57
#Mann= 3 , 0 , 0
       0      .1       0   161.6    .045       0   190.1      .1       0
Bank Sta=161.6,190.1
XS Rating Curve= 0 ,0
Exp/Cntr=0.3,0.1

Type RM Length L Ch R = 1 ,5188.2  ,262.8,293.1,323.5
XS GIS Cut Line= 3
     1620633.849      566451.951       1620650.4       566244.64
       1620894.9      565862.795
#Sta/Elev= 30
       0  583.62    94.5  580.78     104  580.14   113.4  578.28   122.9  575.46
   132.4  573.14   141.8  572.99   150.3  575.85   160.7  581.78   179.6  593.51
     208     610   217.6  614.05   227.3  617.66   236.9  620.42   285.2   632.4
   314.1  638.57   352.7  645.46   391.3  650.74   410.6     652   429.8  652.68
   478.1  652.55     507  651.41   555.3  647.85   564.9   646.8   574.6  645.38
   603.5  640.17   622.8   635.4   632.4  632.26   642.1  628.62   661.4  620.04
#Mann= 3 , 0 , 0
       0      .1       0   122.9    .045       0   150.3      .1       0
Bank Sta=122.9,150.3
XS Rating Curve= 0 ,0
Exp/Cntr=0.3,0.1

Type RM Length L Ch R = 1 ,4895.1  ,135.7,127.5,119.1
XS GIS Cut Line= 3
     1620682.811      566488.315     1620926.952      566447.083
     1621245.964      566125.277
#Sta/Elev= 30
       0  583.26   133.3  579.87   142.8  578.03   152.4  574.83   161.9  572.39
   171.4  572.49   180.9  575.05   190.5  578.18     200   580.2   209.5  581.11
     219  581.46   257.2  580.83   286.2  582.28     344  586.68   392.2  589.93
   401.9  590.79   411.5  592.35   421.1  595.03   430.8  598.37   507.9  627.59
   527.2  634.58   536.8  637.76   556.1  643.42   594.7  651.45   633.2     661
   642.9  663.08   652.5  664.79   662.2  666.12   681.4  668.24   700.7     670
#Mann= 3 , 0 , 0
       0     .06       0   152.4    .045       0   190.5     .06       0
Bank Sta=152.4,190.5
XS Rating Curve= 0 ,0
Exp/Cntr=0.3,0.1

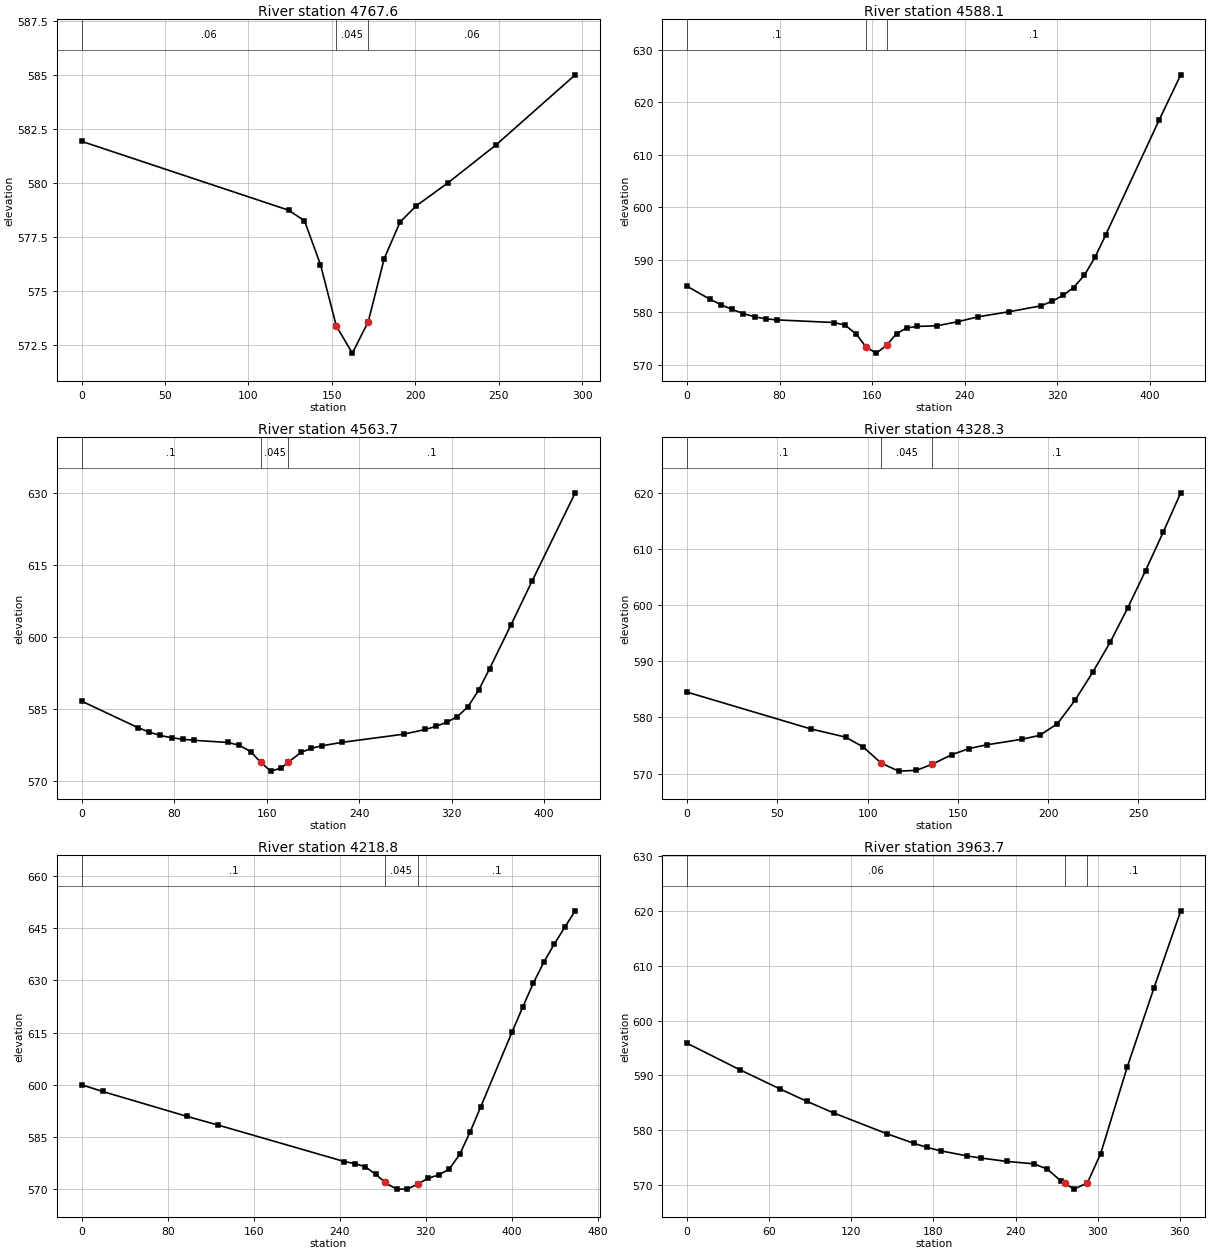
Type RM Length L Ch R = 1 ,4767.6  ,188,179.5,170.8
XS GIS Cut Line= 2
     1620768.315      566660.407     1621023.523      566510.668
#Sta/Elev= 13
       0  581.93   124.1  578.74   133.6  578.25   143.2  576.22   152.7  573.37
   162.3  572.12   171.8  573.57   181.4   576.5   190.9  578.19   200.4  578.93
   219.5     580   248.2  581.75   295.9  585.01
#Mann= 3 , 0 , 0
       0     .06       0   152.7    .045       0   171.8     .06       0
Bank Sta=152.7,171.8
XS Rating Curve= 0 ,0
Exp/Cntr=0.3,0.1

Type RM Length L Ch R = 1 ,4588.1  ,24.5,24.4,24.5
XS GIS Cut Line= 5
     1620983.896      566867.526     1621022.612      566726.553
     1621065.841      566671.345      1621127.82      566664.574
     1621258.539       566594.68
#Sta/Elev= 30
       0  584.99    19.5  582.55    29.2  581.49      39  580.57    48.7  579.78
    58.5  579.17    68.2  578.78      78  578.58   126.7  578.09   136.4  577.62
   146.2   575.9     155  573.36   163.7  572.26   172.5  573.75   181.2  575.99
     190  577.06   198.8  577.34   216.3  577.47   234.1  578.24   251.9  579.19
   278.7  580.15   306.4  581.28   315.7  582.15     325  583.24   334.2  584.75
   343.5  587.07   352.8  590.52     362  594.76   408.4  616.71   426.9  625.24
#Mann= 3 , 0 , 0
       0      .1       0     155    .045       0   172.5      .1       0
Bank Sta=155,172.5
XS Rating Curve= 0 ,0
Exp/Cntr=0.3,0.1

Type RM Length L Ch R = 1 ,4563.7  ,223.6,235.4,247.2
XS GIS Cut Line= 5
     1621000.563      566885.234     1621039.278      566744.262
     1621082.507      566689.053     1621144.487      566682.282
     1621275.206      566612.388
#Sta/Elev= 29
       0  586.57    48.7  581.05    58.5  580.12    68.2  579.41      78  578.93
    87.7  578.62    97.5   578.4   126.7  577.95   136.4  577.36   146.2  576.06
     155  573.78   163.6  571.98   172.5  572.61   178.6  573.83     190  575.91
   198.8  576.75   207.6  577.25   225.2  577.98   278.7  579.69   297.2  580.66
   306.4  581.32   315.7  582.16     325  583.35   334.2  585.42   343.5  588.91
   352.8  593.31   371.3  602.45   389.8  611.71   426.9     630
#Mann= 3 , 0 , 0
       0      .1       0     155    .045       0   178.6      .1       0
Bank Sta=155,178.6
XS Rating Curve= 0 ,0
Exp/Cntr=0.3,0.1

Type RM Length L Ch R = 1 ,4328.3  ,109,109.5,110.1
XS GIS Cut Line= 2
     1621073.002      566931.241     1621324.632      566823.982
#Sta/Elev= 21
       0   584.5    68.4  577.96    87.9  576.48    97.7   574.7   107.5  571.86
   117.2  570.43     127  570.57   135.9  571.67   146.5  573.34   156.3  574.46
   166.1  575.12   185.6  576.11   195.4  576.81   205.2  578.88   214.9  583.04
   224.7  588.02   234.5  593.44   244.2  599.55     254  606.14   263.8     613
   273.5     620
#Mann= 3 , 0 , 0
       0      .1       0   107.5    .045       0   135.9      .1       0
Bank Sta=107.5,135.9
XS Rating Curve= 0 ,0
Exp/Cntr=0.3,0.1

Type RM Length L Ch R = 1 ,4218.8  ,255.1,255.1,255
XS GIS Cut Line= 2
     1620975.203      567083.342     1621401.779      566914.157
#Sta/Elev= 26
       0     600    19.5  598.08    97.6  590.95   126.9  588.42   244.1  577.95
   253.9  577.33   263.6  576.47   273.4  574.27   282.2  571.93   283.2  571.66
   292.9  570.01   302.7  570.02   312.4  571.44   322.2  573.14     332   574.1
   341.7  575.72   351.5  580.01   361.3  586.52     371  593.62   400.3  615.27
   410.1  622.32   419.8  629.13   429.6  635.19   439.4  640.43   449.1  645.26
   458.9     650
#Mann= 3 , 0 , 0
       0      .1       0   282.2    .045       0   312.4      .1       0
Bank Sta=282.2,312.4
XS Rating Curve= 0 ,0
Exp/Cntr=0.3,0.1

Type RM Length L Ch R = 1 ,3963.7  ,208.4,197.2,186
XS GIS Cut Line= 2
     1621113.016      567300.909     1621447.643      567166.194
#Sta/Elev= 22
       0  595.86      39  590.98    68.2   587.5    87.7  585.26   107.2  583.15
   146.2  579.35   165.7  577.63   175.5  576.87   185.2  576.26   204.7  575.33
   214.5  574.95     234  574.32   253.5  573.89   263.2  572.92     273   570.8
   275.9  570.35   282.7  569.28   292.5  570.41   302.2  575.76   321.7  591.61
   341.2  605.98   360.7     620
#Mann= 3 , 0 , 0
       0     .06       0   275.9    .045       0   292.5      .1       0
Bank Sta=275.9,292.5
XS Rating Curve= 0 ,0
Exp/Cntr=0.3,0.1

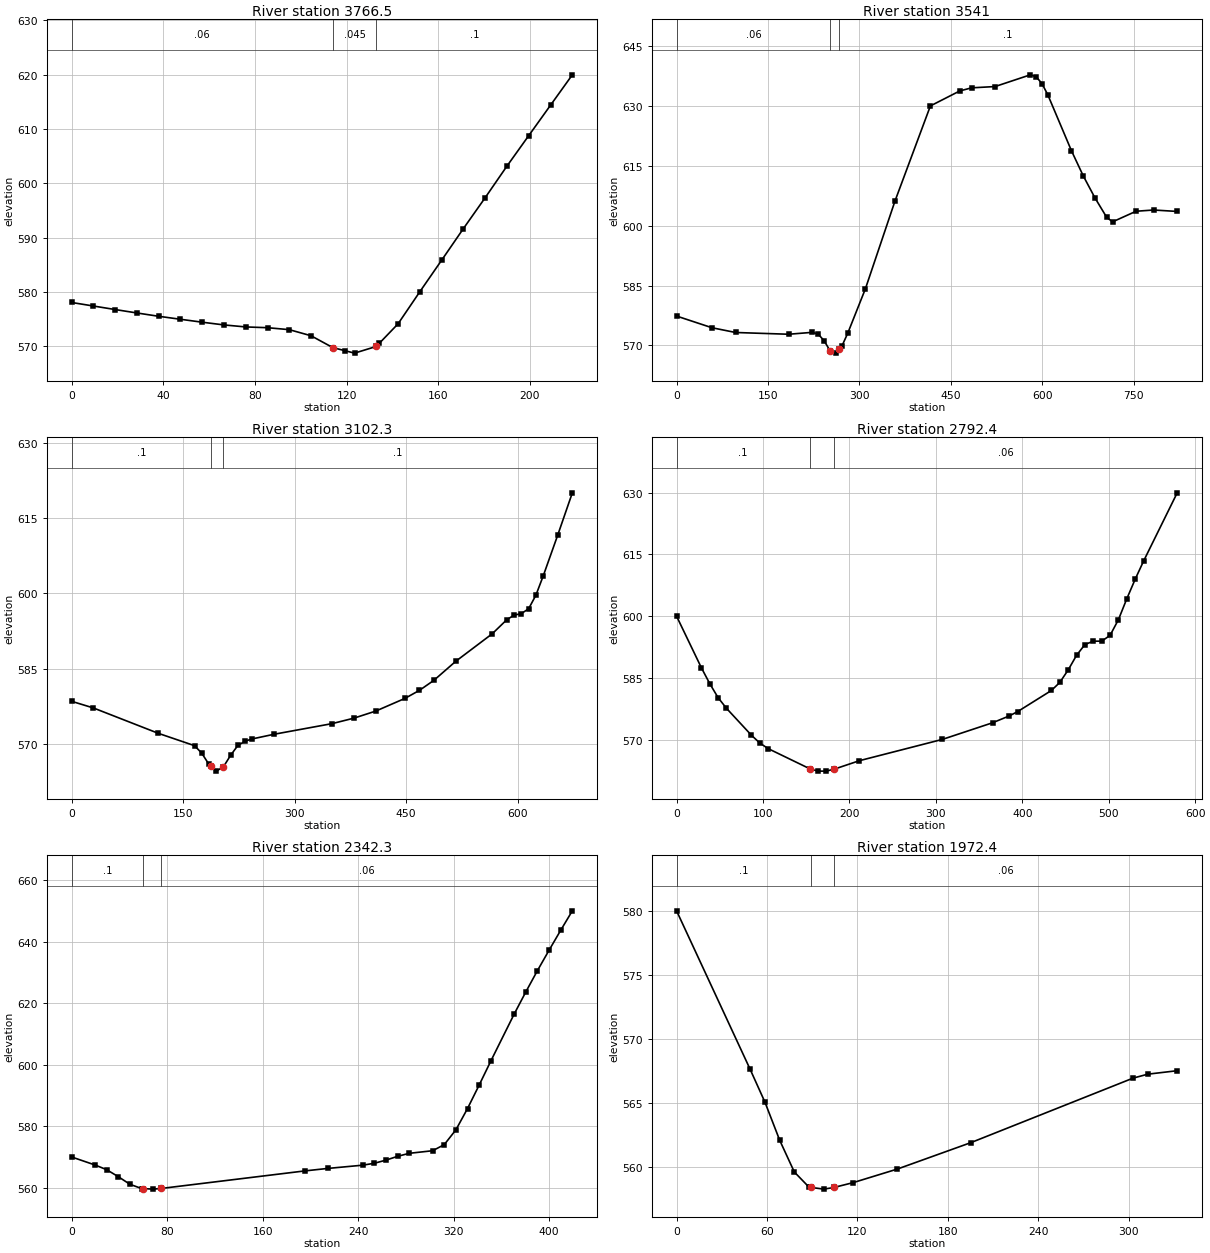
Type RM Length L Ch R = 1 ,3766.5  ,227,225.4,223.8
XS GIS Cut Line= 2
     1621410.719       567449.47     1621550.776      567281.678
#Sta/Elev= 26
       0   578.1     9.5  577.45      19   576.8    28.5  576.17      38  575.56
    47.5  575.01      57  574.47    66.5  573.97      76   573.6    85.5  573.46
      95   573.1   104.5  571.98     114   569.8   119.3  569.23   123.5  568.78
     133  570.01   134.3  570.58   142.5  574.17     152  580.07   161.6  585.92
     171  591.68   180.6  597.42     190  603.17   199.6  608.83   209.1  614.42
   218.6     620
#Mann= 3 , 0 , 0
       0     .06       0     114    .045       0     133      .1       0
Bank Sta=114,133
XS Rating Curve= 0 ,0
Exp/Cntr=0.3,0.1

Type RM Length L Ch R = 1 ,3541    ,405.4,438.7,471.8
XS GIS Cut Line= 3
     1621523.172      567692.836     1621767.217       567355.19
     1622170.115       567313.38
#Sta/Elev= 30
       0  577.35    58.1  574.42    96.9  573.23   184.1  572.79   222.8  573.27
   232.5  572.82   242.2  571.16     252  568.62   261.6  568.06     267  569.03
   271.3   569.8     281  573.07     310  584.21   358.5  606.17   416.6     630
   464.8  633.75   484.1  634.53   522.7  634.85   580.6  637.79   590.2  637.31
   599.8  635.58   609.5  632.72   648.1  618.78   667.4   612.5   686.6  606.99
   705.9   602.1   715.6  600.95   754.2  603.61   783.1  603.92   821.7  603.56
#Mann= 3 , 0 , 0
       0     .06       0     252    .045       0     267      .1       0
Bank Sta=252,267
XS Rating Curve= 0 ,0
Exp/Cntr=0.3,0.1

Type RM Length L Ch R = 1 ,3102.3  ,329.2,309.9,289.3
XS GIS Cut Line= 3
     1621514.886      567720.737     1621784.041      567876.888
     1622144.911      567911.598
#Sta/Elev= 30
       0  578.48    29.2  577.16   116.7   572.1   165.3  569.65     175  568.16
   184.8   565.9   187.2  565.57   194.5  564.58   204.2  565.44   213.9  567.74
   223.6  569.69   233.4  570.55   243.1     571   272.3  571.92   350.4  574.04
   379.8  575.13   409.2  576.54   448.4  579.06   467.9  580.66   487.5  582.67
   516.9  586.46   565.9  591.93   585.5  594.73   595.3  595.64   605.1  595.95
   614.9  596.92   624.7  599.62   634.5  603.44   654.1   611.6   673.7     620
#Mann= 3 , 0 , 0
       0      .1       0   187.2    .045       0   204.2      .1       0
Bank Sta=187.2,204.2
XS Rating Curve= 0 ,0
Exp/Cntr=0.3,0.1

Type RM Length L Ch R = 1 ,2792.4  ,434.5,450.1,465
XS GIS Cut Line= 3
      1621536.47       568098.85     1621862.108      568013.706
     1622099.964      568061.952
#Sta/Elev= 30
       0     600    28.8  587.42    38.5  583.57    48.1  580.18    57.7  577.62
    86.6  571.07    96.2  569.19   105.8  567.83   153.9  562.94   163.5  562.34
   173.1  562.34   182.7  562.84   211.6  564.88   307.7  570.06   365.7   574.1
   385.1  575.77   394.8  576.83   433.7  581.94   443.4  583.89   453.1  586.92
   462.8  590.48   472.5  593.11   482.2  593.93   491.9  593.93   501.6  595.33
   511.3  599.17     521  604.25   530.8  609.05   540.4   613.4   579.3  629.99
#Mann= 3 , 0 , 0
       0      .1       0   153.9    .045       0   182.7     .06       0
Bank Sta=153.9,182.7
XS Rating Curve= 0 ,0
Exp/Cntr=0.3,0.1

Type RM Length L Ch R = 1 ,2342.3  ,356.8,369.9,383
XS GIS Cut Line= 2
     1621535.391      568394.716     1621917.228      568568.191
#Sta/Elev= 28
       0     570    19.5  567.41    29.3  565.88      39  563.61    48.8  561.13
    58.5  559.76    59.8  559.73    68.3  559.56    74.8  559.77   195.1  565.47
   214.6  566.29   243.8  567.34   253.6  567.97   263.3  568.99   273.1  570.23
   282.8   571.2   302.4  572.04   312.1  574.02   321.9  578.85   331.6  585.75
   341.4  593.42   351.1  601.17   370.6  616.39   380.4  623.62   390.1  630.53
   399.9  637.19   409.6  643.64   419.4     650
#Mann= 3 , 0 , 0
       0      .1       0    59.8    .045       0    74.8     .06       0
Bank Sta=59.8,74.8
XS Rating Curve= 0 ,0
Exp/Cntr=0.3,0.1

Type RM Length L Ch R = 1 ,1972.4  ,378,374.1,369.7
XS GIS Cut Line= 2
     1621317.397      568600.573     1621504.035      568875.251
#Sta/Elev= 15
       0     580    48.8  567.62    58.6  565.06    68.4  562.08    78.1   559.6
    87.9  558.41    89.4  558.39    97.7  558.26   104.4  558.39   117.2  558.77
   146.5  559.83   195.4   561.9   302.8  566.93   312.6  567.24   332.1  567.51
#Mann= 3 , 0 , 0
       0      .1       0    89.4    .045       0   104.4     .06       0
Bank Sta=89.4,104.4
XS Rating Curve= 0 ,0
Exp/Cntr=0.3,0.1

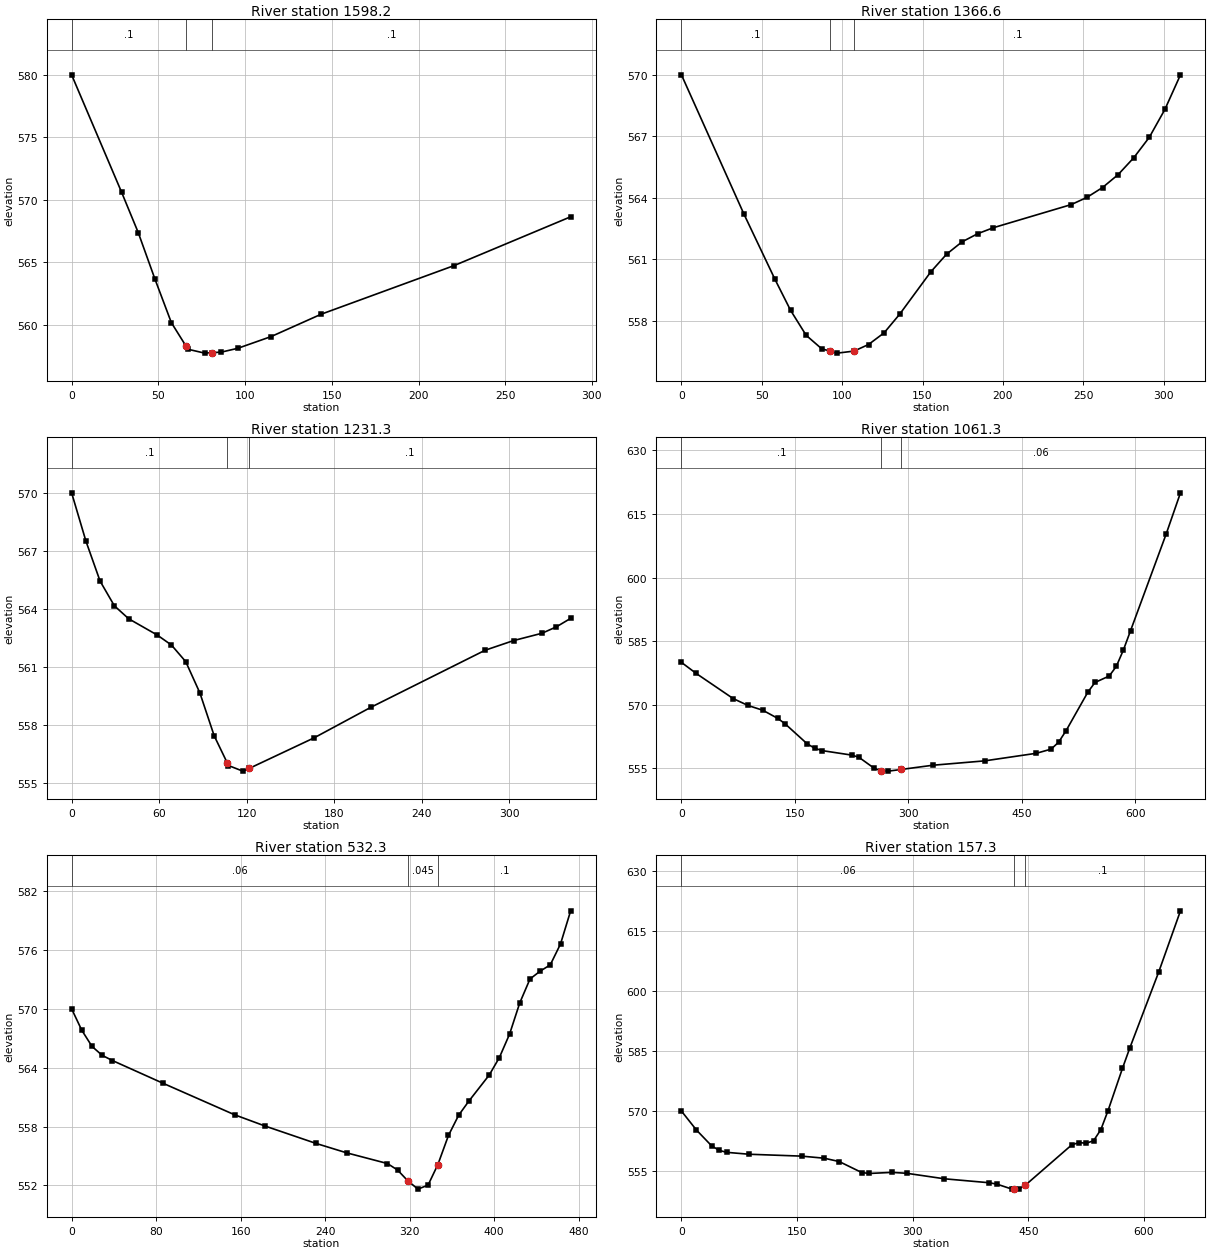
Type RM Length L Ch R = 1 ,1598.2  ,239.4,231.6,224.4
XS GIS Cut Line= 2
     1621025.782       568838.16     1621226.257      569044.522
#Sta/Elev= 15
       0     580    28.8  570.61    38.4  567.38      48  563.67    57.5  560.17
      66  558.28    67.1  558.04    76.7  557.73      81  557.77    86.3  557.81
    95.9  558.12   115.1  559.06   143.8  560.84   220.6  564.74   287.7  568.64
#Mann= 3 , 0 , 0
       0      .1       0      66    .045       0      81      .1       0
Bank Sta=66,81
XS Rating Curve= 0 ,0
Exp/Cntr=0.3,0.1

Type RM Length L Ch R = 1 ,1366.6  ,136.3,135.3,133.6
XS GIS Cut Line= 2
     1620912.856      569040.194     1621179.766      569198.836
#Sta/Elev= 25
       0  569.99    38.8  563.21    58.2  560.01    67.9   558.5    77.6  557.28
    87.3  556.62    92.4  556.51      97  556.41   107.4  556.51   116.4  556.83
   126.1   557.4   135.8  558.31   155.2  560.38     165  561.24   174.6  561.84
   184.4  562.24   194.1  562.53   242.6  563.66   252.3  564.01     262  564.49
   271.7  565.12   281.4  565.94   291.1  566.94   300.8   568.3   310.5  569.99
#Mann= 3 , 0 , 0
       0      .1       0    92.4    .045       0   107.4      .1       0
Bank Sta=92.4,107.4
XS Rating Curve= 0 ,0
Exp/Cntr=0.3,0.1

Type RM Length L Ch R = 1 ,1231.3  ,179.2,170.1,160.7
XS GIS Cut Line= 2
     1620804.129       569138.16     1621117.751      569274.557
#Sta/Elev= 21
       0     570     9.8   567.5    19.5  565.43    29.3  564.15    39.1  563.48
    58.6  562.64    68.4  562.12    78.2  561.26    87.9  559.64    97.7  557.42
   106.7  556.01   107.5  555.88   117.3  555.59   121.7  555.73   166.1  557.31
   205.2   558.9   283.4  561.85   302.9  562.35   322.4  562.73   332.2  563.06
     342   563.5
#Mann= 3 , 0 , 0
       0      .1       0   106.7    .045       0   121.7      .1       0
Bank Sta=106.7,121.7
XS Rating Curve= 0 ,0
Exp/Cntr=0.3,0.1

Type RM Length L Ch R = 1 ,1061.3  ,535.9,529,520.8
XS GIS Cut Line= 3
     1620597.654      569348.603     1621125.372      569351.135
     1621246.448      569403.314
#Sta/Elev= 30
       0     580    19.6  577.38    68.4  571.46      88  569.83   107.5  568.71
     127  566.82   136.8  565.54   166.1   560.8   175.9  559.77   185.7  559.19
   224.8  558.13   234.5  557.62   254.1   555.1   263.9  554.39   273.6  554.34
   290.7  554.74   332.3  555.73   400.7  556.76   469.1  558.55   488.6  559.53
   498.4  561.14   508.2  563.82   537.1  572.95   546.6  575.26   565.4  576.78
   574.8  579.05   584.2  582.94   593.6  587.47   640.7  610.29   659.6  620.01
#Mann= 3 , 0 , 0
       0      .1       0   263.9    .045       0   290.7     .06       0
Bank Sta=263.9,290.7
XS Rating Curve= 0 ,0
Exp/Cntr=0.3,0.1

Type RM Length L Ch R = 1 ,532.3   ,370.4,375.1,382.1
XS GIS Cut Line= 2
     1620660.243      569845.419     1621119.815      569735.486
#Sta/Elev= 28
       0     570     9.6  567.82    19.3  566.17    28.9  565.26    38.6  564.73
    86.8   562.4   154.3   559.2   183.2  558.05   231.4  556.28   260.4  555.32
     299  554.23   308.6  553.57   318.2  552.48   327.9  551.62   337.5  552.03
   346.8  554.13   356.8  557.09   366.5  559.16   376.1  560.59   395.4  563.25
     405  565.03   414.7  567.43   424.3   570.6     434  573.04   443.6  573.84
   453.2  574.48   462.9  576.61   472.5  579.99
#Mann= 3 , 0 , 0
       0     .06       0   318.2    .045       0   346.8      .1       0
Bank Sta=318.2,346.8
XS Rating Curve= 0 ,0
Exp/Cntr=0.3,0.1

Type RM Length L Ch R = 1 ,157.3   ,178.5,157.3,133.1
XS GIS Cut Line= 3
     1620716.161      570076.948     1621211.423      570035.567
     1621313.709      569925.449
#Sta/Elev= 30
       0     570    19.5  565.26      39  561.35    48.7  560.21    58.5   559.7
    87.7  559.22   155.9  558.75   185.2  558.23   204.6   557.4   233.9  554.65
   243.6  554.42   272.9  554.69   292.4  554.46   341.1  553.09   399.5   552.1
   409.3  551.75   428.8  550.51   430.9  550.53   438.5  550.61   445.9  551.46
   506.4  561.58   515.8  562.13   525.2  561.97   534.6   562.6     544  565.35
   553.4  570.14   572.1  580.69   581.5  585.71   619.1  604.73   647.3     620
#Mann= 3 , 0 , 0
       0     .06       0   430.9    .045       0   445.9      .1       0
Bank Sta=430.9,445.9
XS Rating Curve= 0 ,0
Exp/Cntr=0.3,0.1

Chan Stop Cuts=-1
Use User Specified Reach Order=0
Composite Channel Slope=5